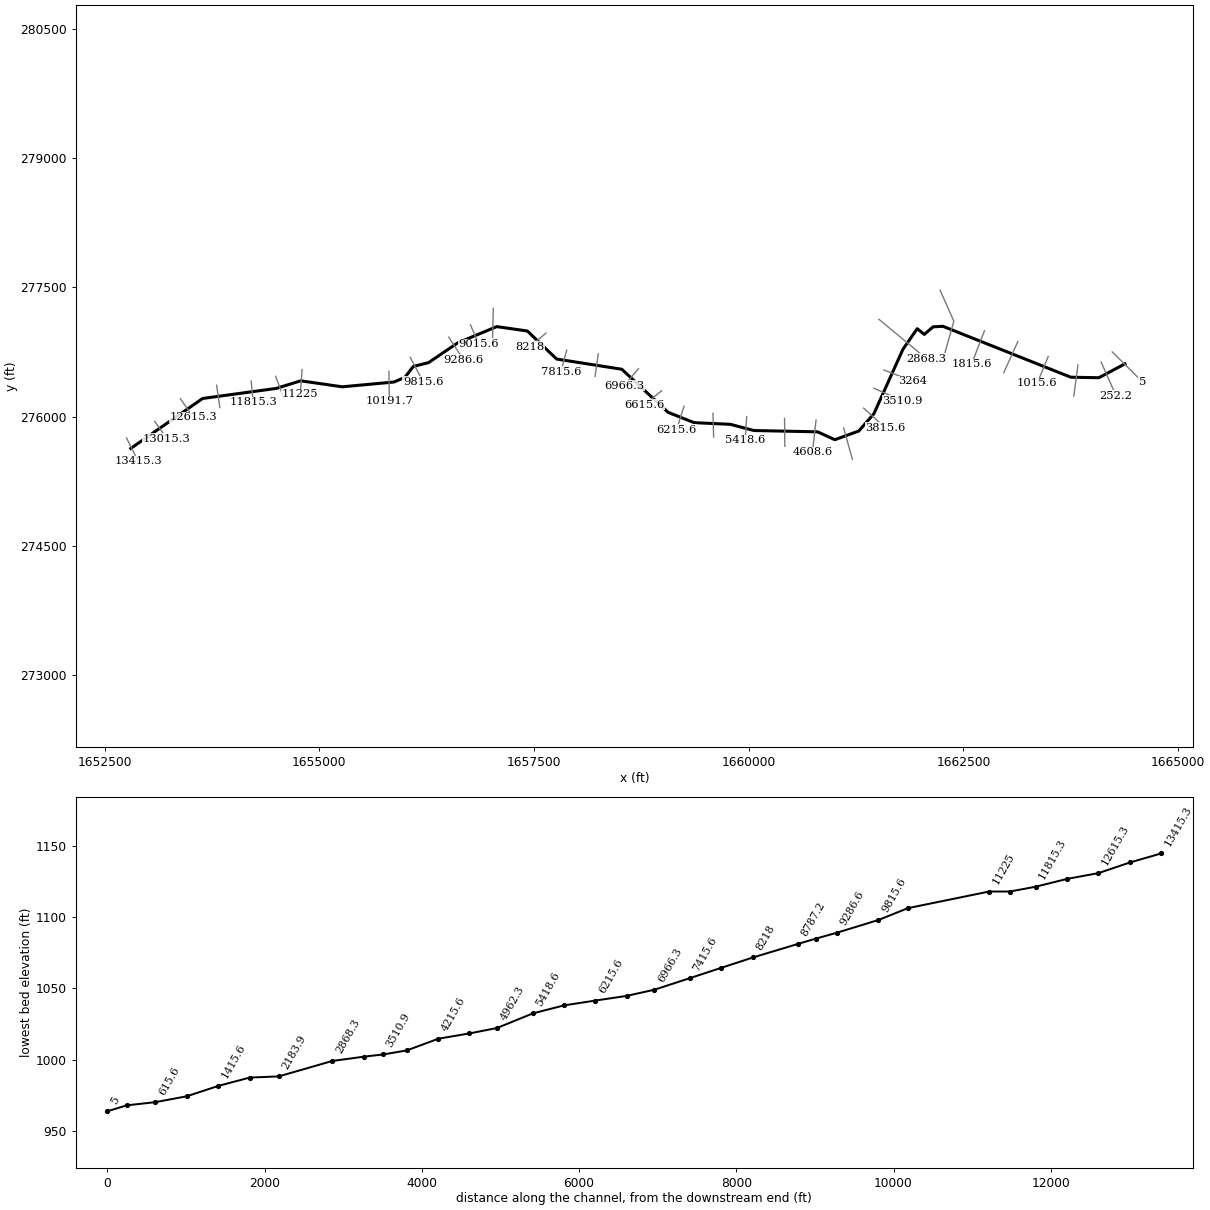
--- RIGHTPNCRK.prj (project) ---

Proj Title=RIGHTPNCRK
Current Plan=p01
Default Exp/Contr=0,0
English Units
Geom File=g01
Flow File=f01
Plan File=p01
BEGIN DESCRIPTION:
END DESCRIPTION:
DSS Export Rating Curves= 0
DSS Export Rating Curve Sorted= 0
DSS Export Volume Flow Curves= 0
DXF OffsetX= 0
DXF OffsetY= 0
DXF ScaleX= 0
DXF ScaleY= 0

--- RIGHTPNCRK.p01 (plan) ---

Plan Title=Floodplain
Program Version=4.00
Geom File=g01
Flow File=f01
K Sum by GR=0
Std Step Tol=0.01
Critical Tol=0.01
Num of Std Step Trials=20
Max Error Tol=0.3
Flow Tol Ratio=0.001
Split Flow NTrial=30
Split Flow Tol=0.02
Split Flow Ratio=0.02
Log Output Level=0
Friction Slope Method=1
Unsteady Friction Slope Method=2
Unsteady Bridges Friction Slope Method=1
Global Log Level=0
CheckData=False
Run HTab=0
Run UNet=0
Run PostProcess=0
UNET Theta=0
UNET Theta Warmup=0
UNET ZTol=0
UNET ZSATol=0
UNET MxIter=0
UNET MaxInSteps=0
UNET DtIC=0
UNET DtMin=0
UNET MaxCRTS=0
UNET WFStab=0
UNET SFStab=0
UNET WFX=0
UNET SFX=0
UNET DSS MLevel=0
UNET DZMax Abort=0
UNET Convert EG Bridges=0
UNET Use Existing IB Tables=0
UNET Froude Limit=0
UNET Froude Power=0
Write IC File=0
Echo Input=False
Echo Output=False
Write Detailed=0

--- RIGHTPNCRK.f01 (steady flow) ---

Flow Title=NFF Regression Equation
Program Version=4.00
Number of Profiles=1
Profile Names=P100yr
River Rch & RM=RIGHTPNCRK,Main      ,13415.3
849.3299
River Rch & RM=RIGHTPNCRK,Main      ,12215.3
941.8351
River Rch & RM=RIGHTPNCRK,Main      ,10191.7
1041.258
River Rch & RM=RIGHTPNCRK,Main      ,9815.6
1106.844
River Rch & RM=RIGHTPNCRK,Main      ,8218
1227.602
River Rch & RM=RIGHTPNCRK,Main      ,5815.6
1310.788
River Rch & RM=RIGHTPNCRK,Main      ,2183.9
1434.570
River Rch & RM=RIGHTPNCRK,Main      ,252.2
1800.176
Boundary for River Rch & Prof#=RIGHTPNCRK,Main      ,1
Up Type=0
Dn Type=3
Dn Slope=0.011334

--- RIGHTPNCRK.g01 (geometry) ---

Geom Title=USGS 10m DEM
Program Version=4.10

River Reach=RIGHTPNCRK      ,Main
Reach XY= 30
     1652804.262       275631.27     1653640.484      276210.371
     1654498.713       276327.35     1654782.472      276415.373
     1655265.443      276345.881     1655868.867      276401.475
     1655996.269       276455.91     1656093.558      276582.154
     1656270.763      276626.166     1656612.433      276856.649
     1657065.291      277044.278     1657422.017      276993.317
     1657762.529      276667.862     1658521.152      276549.725
     1659060.875      276049.381     1659363.166      275930.086
      1659785.91      275910.397     1660059.246      275838.588
     1660800.496      275823.532     1661002.023      275732.033
      1661281.15      275832.797     1661457.197      276034.325
     1661795.392      276782.524     1661961.015      277019.955
     1662043.248      276953.938     1662146.328      277041.961
      1662260.99      277047.752     1663749.281      276457.069
     1664075.894      276451.278     1664379.889      276611.925

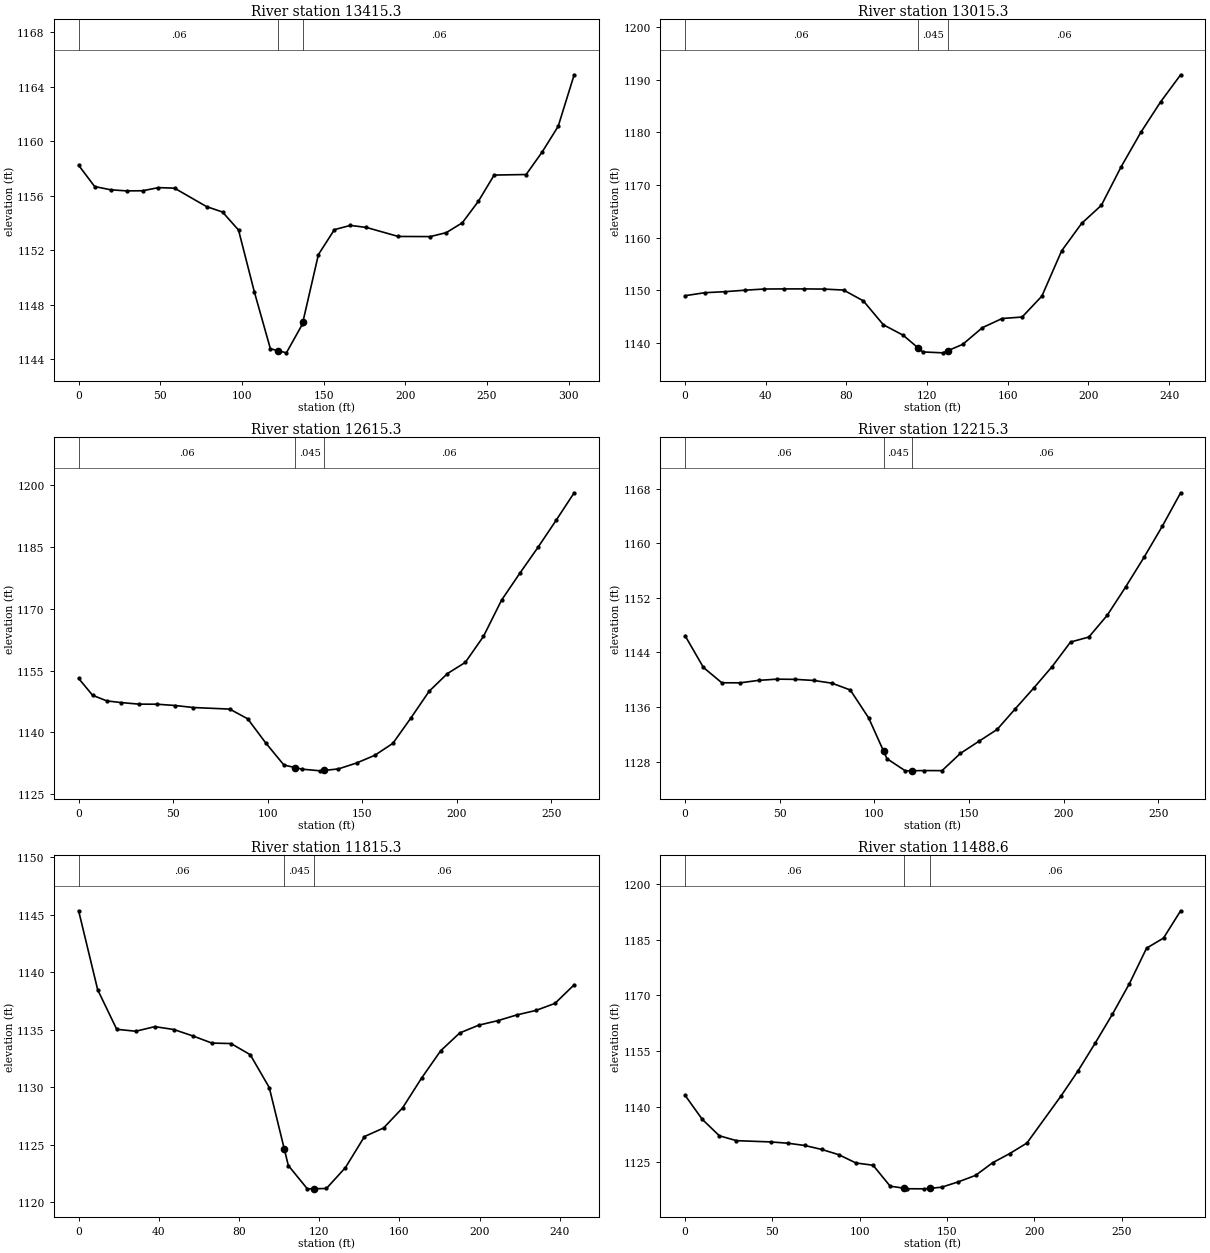
Type RM Length L Ch R = 1 ,13415.3 ,396.5,399.9,403.3
XS GIS Cut Line= 2
     1652755.152      275751.848     1652890.828      275480.498
#Sta/Elev= 30
       0 1158.23     9.8 1156.67    19.6 1156.43    29.4 1156.35    39.2 1156.36
    48.9 1156.59    58.7 1156.55    78.3  1155.2    88.1  1154.8    97.9 1153.48
   107.6 1148.94   117.4 1144.78   122.3 1144.63   127.2 1144.48     137 1146.58
   137.3 1146.74   146.8 1151.68   156.6 1153.51   166.4 1153.82   176.2 1153.67
   195.7 1153.01   215.3    1153   225.1 1153.29   234.9 1154.01   244.7 1155.58
   254.4 1157.51     274 1157.55   283.8  1159.2   293.6 1161.08   303.4 1164.86
#Mann= 3 , 0 , 0
       0     .06       0   122.3    .045       0   137.3     .06       0
Bank Sta=122.3,137.3
XS Rating Curve= 0 ,0
Exp/Cntr=0.3,0.1

Type RM Length L Ch R = 1 ,13015.3 ,400,400,400
XS GIS Cut Line= 2
     1653083.287      275943.521     1653225.104      275742.903
#Sta/Elev= 28
       0 1148.99     9.8 1149.56    19.6 1149.75    29.5 1150.03    39.3 1150.26
    49.1 1150.28      59 1150.28    68.8 1150.25    78.6 1150.06    88.4    1148
    98.3 1143.47   108.1 1141.49   115.3 1139.15   117.9 1138.31   127.8 1138.14
   130.3 1138.55   137.6 1139.74   147.4 1142.92   157.2 1144.66   167.1 1144.94
   176.9 1148.91   186.7 1157.51   196.6 1162.71   206.4 1166.16   216.2 1173.47
     226 1180.03   235.8 1185.81   245.7 1190.94
#Mann= 3 , 0 , 0
       0     .06       0   115.3    .045       0   130.3     .06       0
Bank Sta=115.3,130.3
XS Rating Curve= 0 ,0
Exp/Cntr=0.3,0.1

Type RM Length L Ch R = 1 ,12615.3 ,410.6,400,389.4
XS GIS Cut Line= 3
     1653381.188      276207.543       1653394.1      276189.349
     1653532.874      275993.804
#Sta/Elev= 30
       0 1153.12     7.4 1149.03    14.9 1147.67    22.3 1147.27    31.9 1146.88
    41.5 1146.86    51.1 1146.55    60.7 1146.06    79.9 1145.68    89.4 1143.33
      99 1137.44   108.6 1132.09   114.7 1131.46   118.2  1131.1   127.8 1130.69
   129.7 1130.78   137.4 1131.16     147 1132.59   156.6 1134.45   166.2 1137.36
   175.8 1143.56   185.4 1150.01     195 1154.28   204.5 1157.01   214.1 1163.31
   223.7 1172.13   233.3 1178.62   242.9 1184.91   252.5 1191.47   262.1 1198.19
#Mann= 3 , 0 , 0
       0     .06       0   114.7    .045       0   129.7     .06       0
Bank Sta=114.7,129.7
XS Rating Curve= 0 ,0
Exp/Cntr=0.3,0.1

Type RM Length L Ch R = 1 ,12215.3 ,401.1,400,398.9
XS GIS Cut Line= 2
     1653803.744      276364.054     1653841.538      276104.895
#Sta/Elev= 30
       0 1146.45     9.7 1141.79    19.4 1139.55    29.1 1139.54    38.8  1139.9
    48.5 1140.08    58.2 1140.05    67.9 1139.89    77.6 1139.49    87.3 1138.49
      97  1134.4   104.9 1129.52   106.7 1128.41   116.4 1126.63   119.9 1126.64
   126.1 1126.67   135.8 1126.66   145.5 1129.19   155.2 1130.95   164.9  1132.7
   174.6 1135.76   184.3 1138.79     194 1141.93   203.7 1145.52   213.4 1146.26
   223.1 1149.45   232.8 1153.59   242.5 1157.93   252.2 1162.51   261.9 1167.42
#Mann= 3 , 0 , 0
       0     .06       0   104.9    .045       0   119.9     .06       0
Bank Sta=104.9,119.9
XS Rating Curve= 0 ,0
Exp/Cntr=0.3,0.1

Type RM Length L Ch R = 1 ,11815.3 ,320.7,326.6,332.6
XS GIS Cut Line= 2
     1654205.991      276413.251     1654229.733      276167.239
#Sta/Elev= 29
       0 1145.34     9.5 1138.47      19 1135.03    28.5 1134.86      38 1135.26
    47.5 1135.01      57 1134.45    66.5 1133.83      76 1133.79    85.6 1132.82
    95.1 1129.96   102.6 1124.61   104.6 1123.18   114.1 1121.15   117.6 1121.16
   123.6 1121.18   133.1    1123   142.6  1125.7   152.1 1126.44   161.6 1128.19
   171.1 1130.79   180.6 1133.16   190.1 1134.71   199.6 1135.39   209.1 1135.78
   218.6 1136.28   228.1 1136.67   237.6 1137.28   247.2  1138.9
#Mann= 3 , 0 , 0
       0     .06       0   102.6    .045       0   117.6     .06       0
Bank Sta=102.6,117.6
XS Rating Curve= 0 ,0
Exp/Cntr=0.3,0.1

Type RM Length L Ch R = 1 ,11488.6 ,273.2,263.5,253.8
XS GIS Cut Line= 2
     1654490.798      276467.673     1654590.737      276202.142
#Sta/Elev= 30
       0 1143.02     9.8 1136.57    19.6 1132.12    29.4  1130.8    48.9 1130.46
    58.7 1130.12    68.5  1129.5    78.3 1128.42      88 1127.01    97.8 1124.78
   107.6 1124.17   117.4 1118.52   125.1 1117.98   127.2 1117.83     137  1117.8
   140.1 1117.94   146.8 1118.23   156.5  1119.7   166.3 1121.43   176.1 1124.85
   185.9 1127.33   195.7 1130.16   215.2 1142.85     225 1149.66   234.8 1157.14
   244.6 1164.88   254.4  1173.2   264.2 1182.74   273.9 1185.47   283.7 1192.83
#Mann= 3 , 0 , 0
       0     .06       0   125.1    .045       0   140.1     .06       0
Bank Sta=125.1,140.1
XS Rating Curve= 0 ,0
Exp/Cntr=0.3,0.1

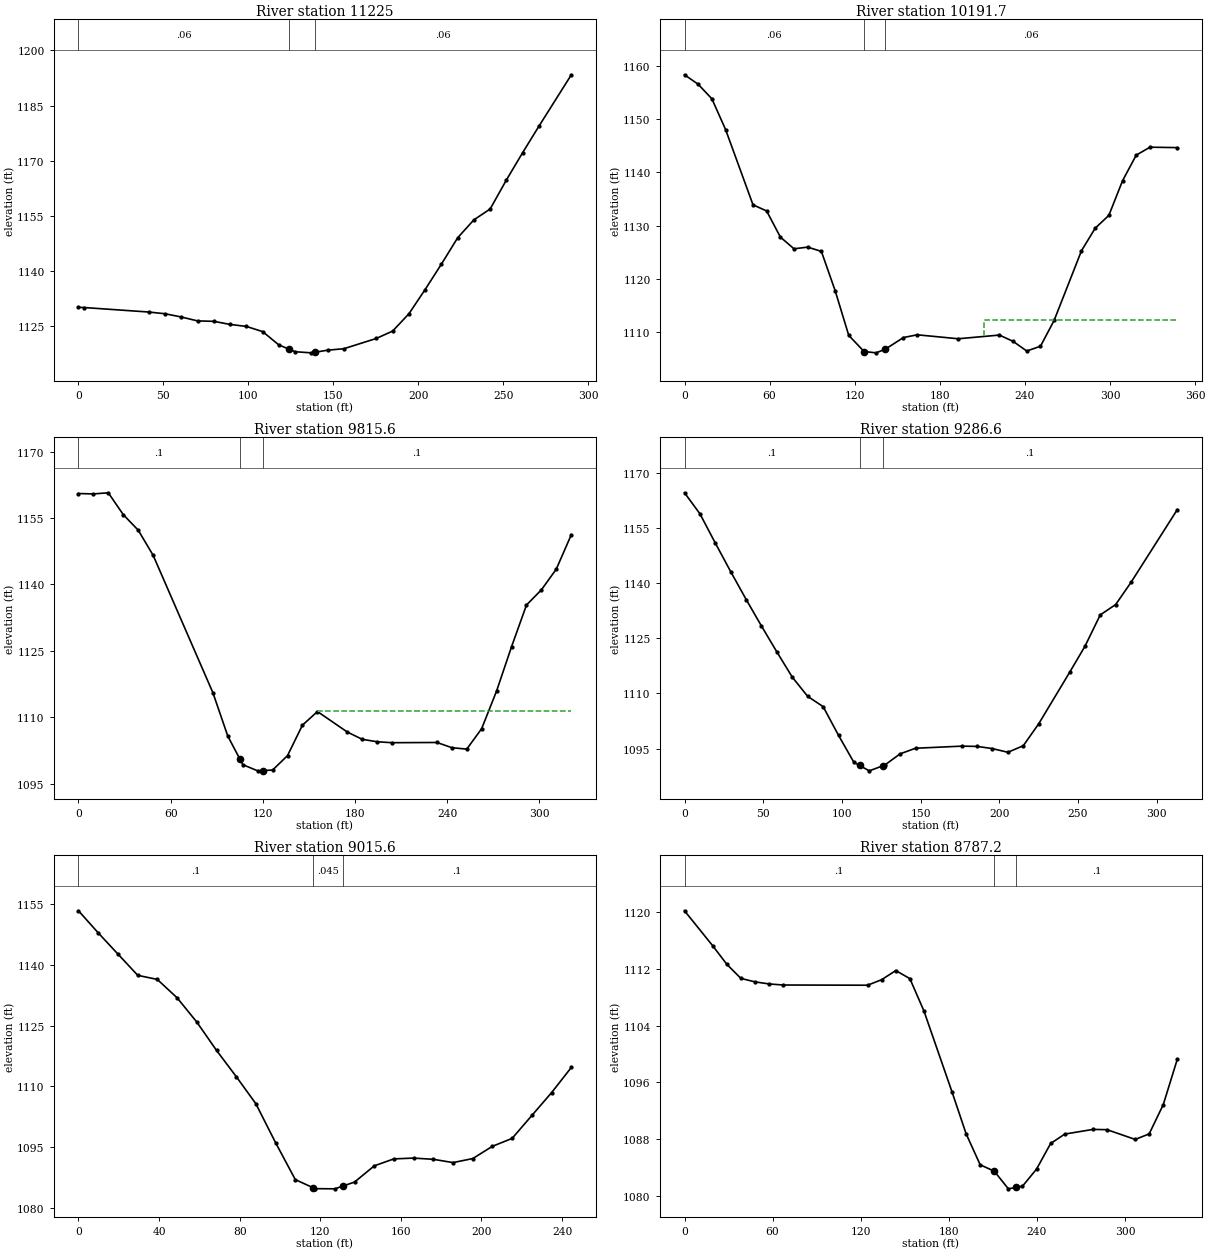
Type RM Length L Ch R = 1 ,11225   ,1031.3,1033.2,1035.2
XS GIS Cut Line= 3
     1654798.527      276546.581     1654798.305      276543.468
     1654777.855      276257.175
#Sta/Elev= 29
       0 1130.16     3.1 1130.12    41.4 1128.89      51 1128.42    60.5 1127.54
    70.1 1126.48    79.7 1126.36    89.2 1125.52    98.8 1124.98   108.4 1123.57
   117.9 1119.96     124 1118.78   127.5  1118.1   137.1  1117.8     139 1117.94
   146.6 1118.52   156.2 1118.92   175.3 1121.71   184.9 1123.71   194.5 1128.42
     204 1134.98   213.6  1141.9   223.2 1149.08   232.7 1153.93   242.3 1156.89
   251.9  1164.8   261.4 1172.18     271 1179.38   290.1 1193.37
#Mann= 3 , 0 , 0
       0     .06       0     124    .045       0     139     .06       0
Bank Sta=124,139
XS Rating Curve= 0 ,0
Exp/Cntr=0.3,0.1

Type RM Length L Ch R = 1 ,10191.7 ,365.5,376.1,386.7
XS GIS Cut Line= 2
     1655809.606      276525.308     1655815.161       276177.86
#Sta/Elev= 30
       0 1158.28     9.6 1156.51    19.3 1153.78      29 1147.99    48.3 1133.91
    57.9 1132.76    67.6 1127.86    77.2 1125.67    86.9 1125.98    96.5 1125.18
   106.2 1117.83   115.8 1109.44   126.6 1106.42   135.1 1106.17   141.6 1106.86
   154.4 1109.04   164.1 1109.55     193 1108.81     222  1109.5   231.7 1108.32
   241.3 1106.51     251 1107.41   260.6 1112.24   279.9  1125.3   289.6 1129.54
   299.2 1131.93   308.9 1138.45   318.5 1143.22   328.2 1144.71   347.5 1144.63
#Mann= 3 , 0 , 0
       0     .06       0   126.6    .045       0   141.6     .06       0
#XS Ineff= 2 , 0
                          210.88         1112.31
Permanent Ineff=
       F       F
Bank Sta=126.6,141.6
XS Rating Curve= 0 ,0
Exp/Cntr=0.3,0.1

Type RM Length L Ch R = 1 ,9815.6  ,527,529.1,531.1
XS GIS Cut Line= 2
     1656056.858      276690.066     1656206.983      276406.496
#Sta/Elev= 30
       0 1160.55     9.7 1160.46    19.4 1160.72    29.2 1155.76    38.9 1152.26
    48.6 1146.59    87.5 1115.54    97.2 1105.73     105 1100.58     107 1099.26
   116.7 1097.87     120 1097.93   126.4 1098.05   136.1 1101.31   145.8 1108.19
   155.6 1111.27     175 1106.65   184.7    1105   194.5 1104.44   204.2 1104.23
   233.4 1104.28   243.1  1103.1   252.8 1102.78   262.5  1107.4   272.2 1115.89
     282 1125.96   291.7 1135.36   301.4 1138.78   311.1 1143.47   320.9 1151.26
#Mann= 3 , 0 , 0
       0      .1       0     105    .045       0     120      .1       0
#XS Ineff= 2 , 0
                           155.8         1111.32
Permanent Ineff=
       F       F
Bank Sta=105,120
XS Rating Curve= 0 ,0
Exp/Cntr=0.3,0.1

Type RM Length L Ch R = 1 ,9286.6  ,274.7,270.9,267.1
XS GIS Cut Line= 2
     1656505.913      276921.955     1656678.625      276660.708
#Sta/Elev= 30
       0 1164.62     9.8  1158.9    19.6 1150.91    29.4 1143.12    39.2 1135.56
    48.9 1128.36    58.7  1121.3    68.5 1114.43    78.3  1109.2    88.1 1106.42
    97.9 1098.58   107.6 1091.28   111.3  1090.4   117.4 1088.94   126.3 1090.35
   127.2 1090.49     137 1093.56   146.8 1095.09   176.2 1095.66     186 1095.59
   195.7 1094.99   205.5 1093.99   215.3 1095.78   225.1 1101.75   244.7 1115.72
   254.5 1122.86   264.2 1131.38     274  1134.2   283.8 1140.27   313.2 1160.06
#Mann= 3 , 0 , 0
       0      .1       0   111.3    .045       0   126.3      .1       0
#XS Ineff= 2 , 0
                           176.3         1095.63
Permanent Ineff=
       F       F
Bank Sta=111.3,126.3
XS Rating Curve= 0 ,0
Exp/Cntr=0.3,0.1

Type RM Length L Ch R = 1 ,9015.6  ,238.2,228.2,218.2
XS GIS Cut Line= 2
     1656759.077       277064.96     1656856.037       276840.42
#Sta/Elev= 28
       0  1153.3     9.8 1147.85    19.6 1142.62    29.4 1137.39    39.1 1136.38
    48.9 1131.87    58.7 1125.88    68.5 1118.89    78.3 1112.42      88 1105.76
    97.8 1096.15   107.6 1087.04   116.3 1085.06   117.4 1084.81   127.2 1084.76
   131.3 1085.46     137 1086.43   146.8 1090.43   156.5 1092.14   166.3 1092.34
   176.1 1092.04   185.9 1091.23   195.7 1092.23   205.4 1095.24   215.2 1097.19
     225 1102.84   234.8 1108.48   244.6 1114.69
#Mann= 3 , 0 , 0
       0      .1       0   116.3    .045       0   131.3      .1       0
Bank Sta=116.3,131.3
XS Rating Curve= 0 ,0
Exp/Cntr=0.3,0.1

Type RM Length L Ch R = 1 ,8787.2  ,588.3,569.2,550.1
XS GIS Cut Line= 2
     1657025.441      277254.689     1657016.648      276919.082
#Sta/Elev= 29
       0 1120.15    19.2 1115.23    28.8 1112.63    38.4 1110.64      48 1110.15
    57.6 1109.86    67.1 1109.71   124.7 1109.68   134.3 1110.46   143.9 1111.74
   153.5 1110.61   163.1 1106.05   182.2 1094.68   191.8 1088.79   201.4 1084.42
   210.5 1083.57     211 1083.52   220.6 1081.04   225.5 1081.23   230.2 1081.41
   239.8 1083.82   249.4 1087.42     259 1088.74   278.2  1089.4   287.8 1089.36
     307 1087.99   316.5 1088.77   326.1 1092.88   335.7 1099.29
#Mann= 3 , 0 , 0
       0      .1       0   210.5    .045       0   225.5      .1       0
Bank Sta=210.5,225.5
XS Rating Curve= 0 ,0
Exp/Cntr=0.3,0.1

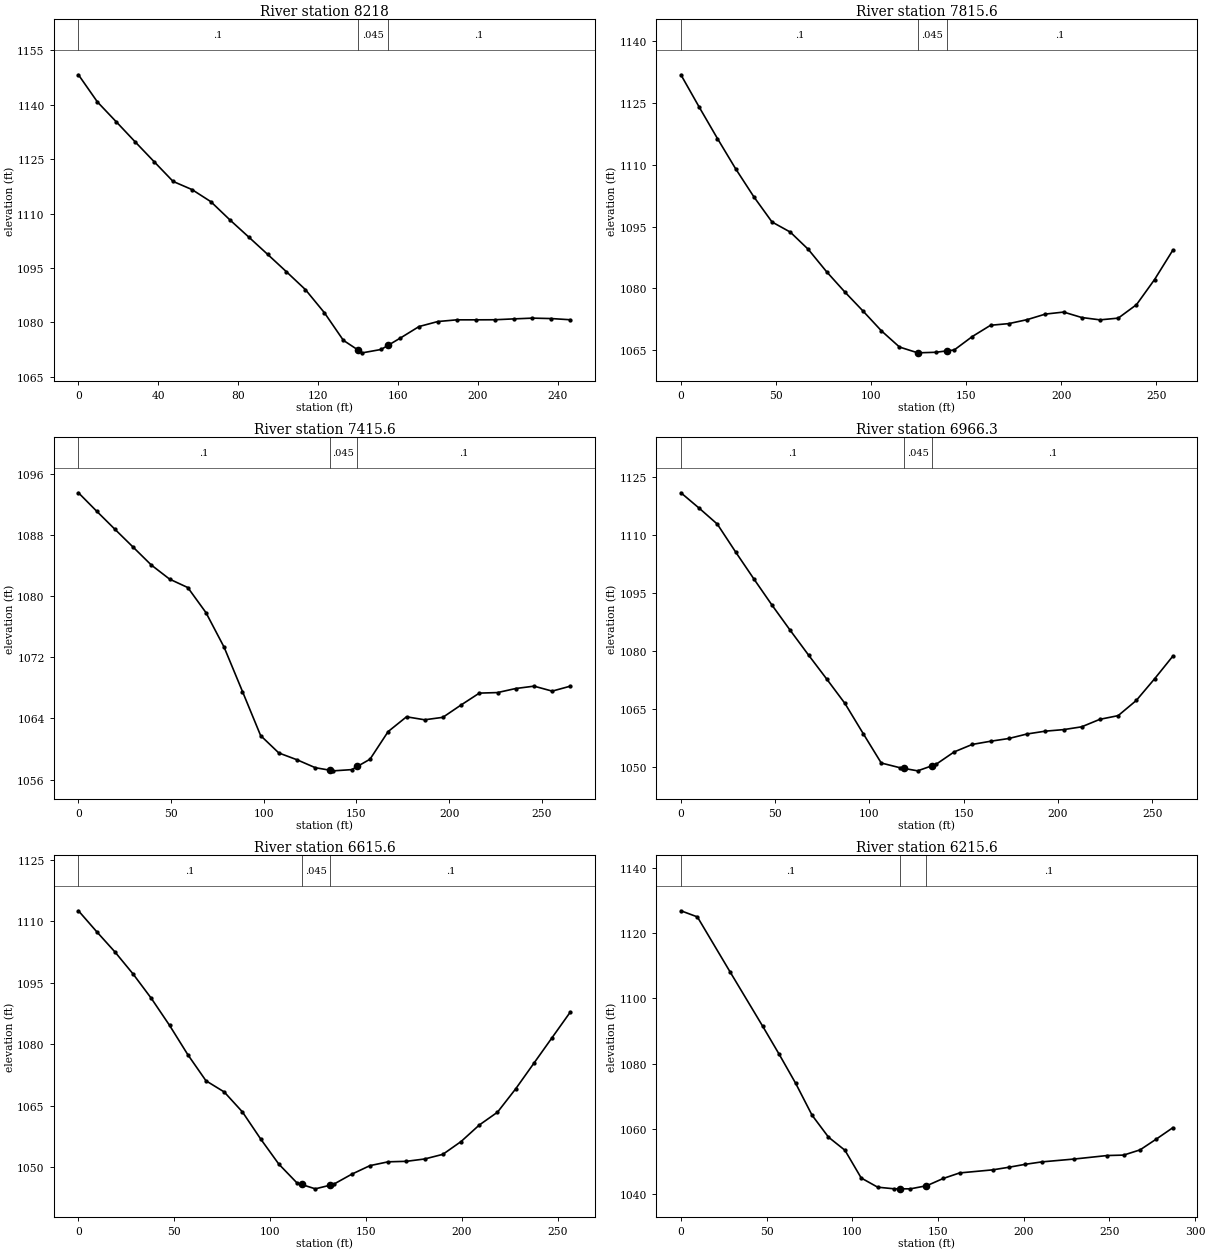
Type RM Length L Ch R = 1 ,8218    ,388.8,402.3,415.8
XS GIS Cut Line= 2
     1657638.034       276968.91     1657450.446      276809.167
#Sta/Elev= 29
       0 1148.28     9.5 1140.79      19 1135.28    28.4 1129.79    37.9 1124.32
    47.4 1118.88    56.9 1116.62    66.3  1113.3    75.8  1108.3    85.3 1103.54
    94.8 1098.75   104.2 1093.96   113.7 1089.04   123.2 1082.67   132.7 1075.06
     140 1072.41   142.2 1071.61   151.6 1072.54     155 1073.65   161.1 1075.64
   170.6 1078.86     180 1080.24   189.5 1080.71     199 1080.71   208.5 1080.73
     218 1080.97   227.4 1081.18   236.9 1081.06   246.4 1080.73
#Mann= 3 , 0 , 0
       0      .1       0     140    .045       0     155      .1       0
Bank Sta=140,155
XS Rating Curve= 0 ,0
Exp/Cntr=0.3,0.1

Type RM Length L Ch R = 1 ,7815.6  ,396.5,399.5,402.4
XS GIS Cut Line= 2
     1657879.934      276770.199     1657811.632      276520.764
#Sta/Elev= 30
       0 1131.83     9.6    1124    19.2 1116.37    28.7 1109.08    38.3 1102.26
    47.9 1096.12    57.5 1093.67      67 1089.46    76.6 1084.05    86.2 1079.13
    95.8 1074.49   105.4 1069.72   114.9 1065.79   124.5 1064.38   124.7 1064.38
   134.1 1064.52   139.7 1064.85   143.7 1065.08   153.2 1068.34   162.8 1071.07
   172.4 1071.47     182 1072.43   191.6 1073.78   201.2 1074.27   210.7 1072.95
   220.3 1072.38   229.9  1072.8   239.5 1076.06     249 1082.16   258.6 1089.28
#Mann= 3 , 0 , 0
       0      .1       0   124.7    .045       0   139.7      .1       0
Bank Sta=124.7,139.7
XS Rating Curve= 0 ,0
Exp/Cntr=0.3,0.1

Type RM Length L Ch R = 1 ,7415.6  ,462,449.6,437.2
XS GIS Cut Line= 2
     1658247.574      276728.258     1658210.182      276465.481
#Sta/Elev= 30
       0 1093.52     9.8 1091.12    19.7 1088.74    29.5 1086.41    39.3 1084.07
    49.2 1082.22      59 1081.12    68.8 1077.84    78.6 1073.31    88.5 1067.52
    98.3 1061.75   108.1 1059.48     118 1058.58   127.8 1057.55   135.5 1057.23
   137.6 1057.14   147.5  1057.3   150.5 1057.72   157.3 1058.66   167.1 1062.28
     177 1064.21   186.8 1063.82   196.6 1064.14   206.4 1065.75   216.3 1067.31
   226.1 1067.38   235.9 1067.91   245.8 1068.22   255.6 1067.57   265.4 1068.22
#Mann= 3 , 0 , 0
       0      .1       0   135.5    .045       0   150.5      .1       0
Bank Sta=135.5,150.5
XS Rating Curve= 0 ,0
Exp/Cntr=0.3,0.1

Type RM Length L Ch R = 1 ,6966.3  ,354.8,350.7,346.5
XS GIS Cut Line= 2
     1658715.315      276556.619     1658546.743      276357.399
#Sta/Elev= 30
       0 1120.86     9.7 1116.88    19.3 1112.78      29  1105.6    38.7 1098.63
    48.3 1091.88      58 1085.35    67.7 1078.98    77.3 1072.82      87  1066.5
    96.7 1058.71   106.3  1051.1     116 1049.91   118.3 1049.71   125.6 1049.08
   133.3  1050.4   135.3 1050.74     145 1053.97   154.6  1055.9   164.3 1056.72
     174 1057.43   183.6 1058.59   193.3 1059.32     203 1059.72   212.6 1060.44
   222.3 1062.38     232 1063.33   241.6 1067.24   251.3 1072.82     261 1078.68
#Mann= 3 , 0 , 0
       0      .1       0   118.3    .045       0   133.3      .1       0
Bank Sta=118.3,133.3
XS Rating Curve= 0 ,0
Exp/Cntr=0.3,0.1

Type RM Length L Ch R = 1 ,6615.6  ,386.9,400,413
XS GIS Cut Line= 2
      1658984.72      276299.967     1658786.171      276137.517
#Sta/Elev= 30
       0 1112.56     9.5 1107.47      19 1102.54    28.5 1097.14      38  1091.2
    47.5 1084.62      57 1077.49    66.5  1071.1      76 1068.38    85.5 1063.51
      95 1056.92   104.5 1050.77     114 1046.17   116.4 1045.81   123.5 1044.75
   131.4 1045.66     133 1045.85   142.5 1048.32     152 1050.41   161.5 1051.34
     171 1051.46   180.5 1052.03     190 1053.16   199.5 1056.28     209 1060.31
   218.5 1063.44     228 1069.14   237.5 1075.39     247 1081.64   256.5 1087.88
#Mann= 3 , 0 , 0
       0      .1       0   116.4    .045       0   131.4      .1       0
Bank Sta=116.4,131.4
XS Rating Curve= 0 ,0
Exp/Cntr=0.3,0.1

Type RM Length L Ch R = 1 ,6215.6  ,392.4,400,407.6
XS GIS Cut Line= 2
     1659246.221      276120.737     1659159.019      275847.315
#Sta/Elev= 28
       0 1126.95     9.6 1125.07    28.7 1108.15    47.8 1091.38    57.4 1082.77
      67 1073.86    76.5 1064.12    86.1 1057.36    95.7 1053.33   105.2  1044.8
   114.8 1041.98   124.4 1041.48   127.8 1041.48   133.9 1041.47   142.8 1042.37
   143.5 1042.44   153.1 1044.67   162.6 1046.36   181.8  1047.3   191.3  1048.1
   200.9 1049.01   210.5 1049.75   229.6 1050.64   248.7 1051.71   258.3 1051.84
   267.9 1053.45   277.4 1056.78     287 1060.26
#Mann= 3 , 0 , 0
       0      .1       0   127.8    .045       0   142.8      .1       0
Bank Sta=127.8,142.8
XS Rating Curve= 0 ,0
Exp/Cntr=0.3,0.1

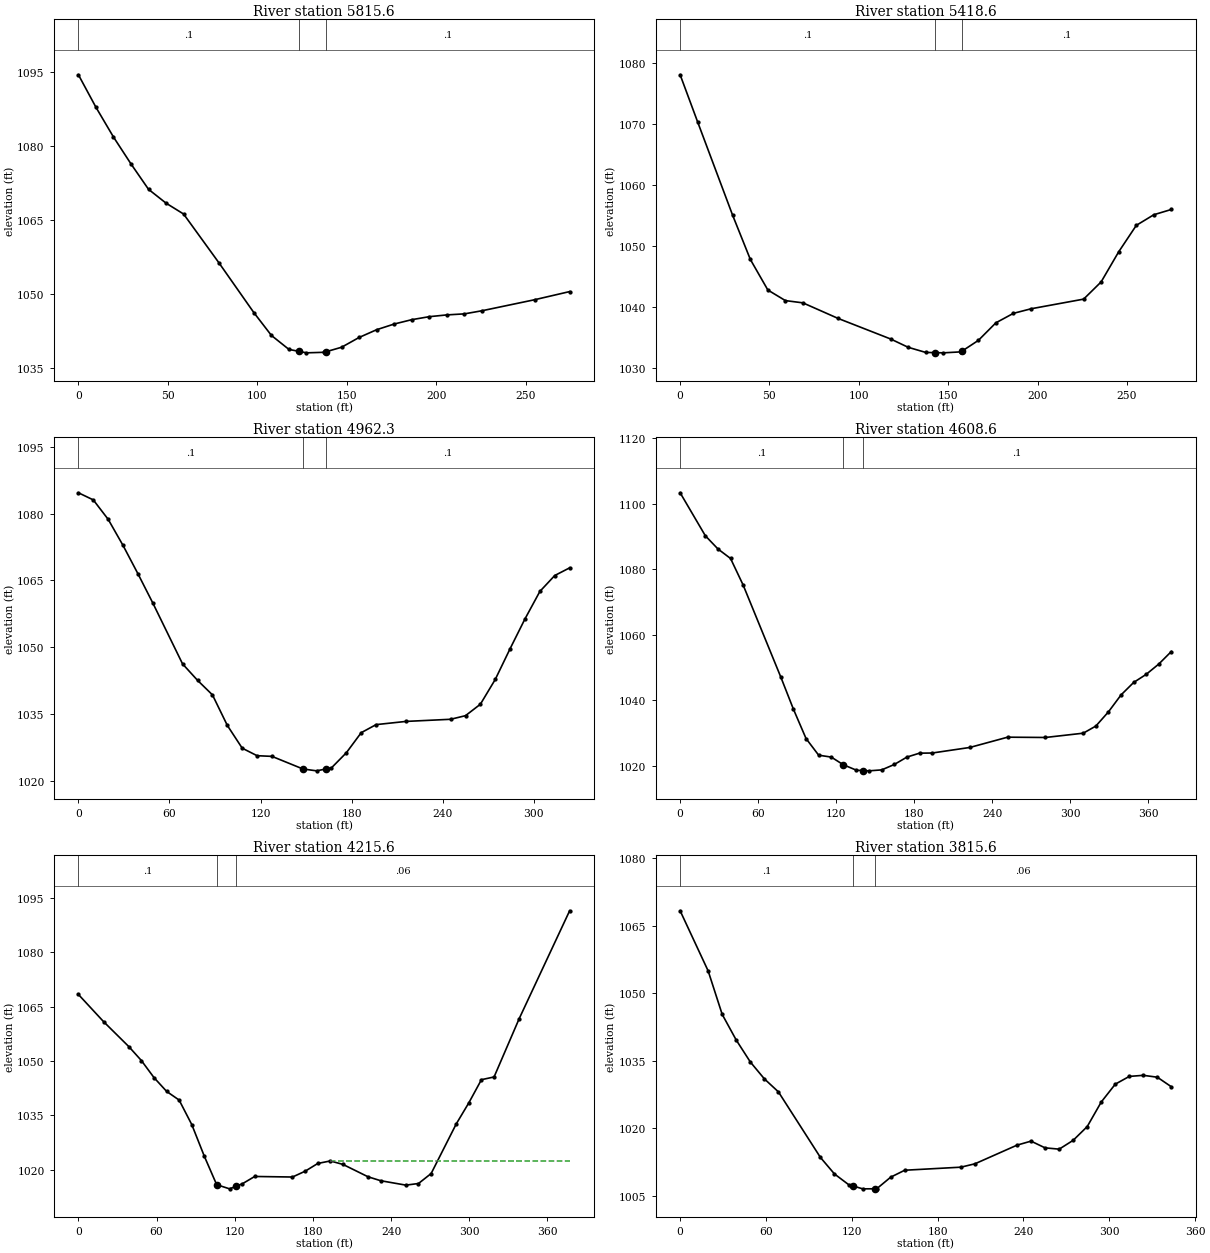
Type RM Length L Ch R = 1 ,5815.6  ,398.9,396.8,394.8
XS GIS Cut Line= 2
     1659583.056      276037.906     1659590.962      275763.421
#Sta/Elev= 26
       0 1094.37     9.8 1087.79    19.6 1081.77    29.4 1076.32    39.2 1071.18
      49 1068.38    58.8 1066.18    78.5 1056.33    98.1 1046.21   107.9  1041.6
   117.7 1038.77   123.3 1038.38   127.5 1038.08   137.3 1038.19   138.3 1038.29
   147.1 1039.21   156.9 1041.19   166.7 1042.76   176.5 1043.91   186.3 1044.79
   196.1  1045.4     206 1045.76   215.8 1045.97   225.6  1046.6     255 1048.83
   274.6 1050.48
#Mann= 3 , 0 , 0
       0      .1       0   123.3    .045       0   138.3      .1       0
Bank Sta=123.3,138.3
XS Rating Curve= 0 ,0
Exp/Cntr=0.3,0.1

Type RM Length L Ch R = 1 ,5418.6  ,454.3,455.9,457.5
XS GIS Cut Line= 2
     1659975.686      275999.875     1659958.687      275725.497
#Sta/Elev= 25
       0 1078.03     9.8  1070.3    29.4    1055    39.3 1047.77    49.1 1042.76
    58.9 1041.03    68.7 1040.66    88.4 1038.11   117.8 1034.74   127.6 1033.38
   137.4 1032.54   142.8  1032.5   147.3 1032.47   157.1 1032.63   157.8 1032.76
   166.9 1034.51   176.7 1037.39   186.5 1038.94   196.4 1039.69   225.8 1041.27
   235.6 1044.09   245.4 1049.01   255.3 1053.36   265.1  1055.1   274.9 1055.96
#Mann= 3 , 0 , 0
       0      .1       0   142.8    .045       0   157.8      .1       0
Bank Sta=142.8,157.8
XS Rating Curve= 0 ,0
Exp/Cntr=0.3,0.1

Type RM Length L Ch R = 1 ,4962.3  ,356.4,353.6,350.9
XS GIS Cut Line= 2
     1660416.421      275978.558     1660419.835      275654.948
#Sta/Elev= 30
       0 1084.69     9.8 1083.09    19.6 1078.73    29.4 1072.86    39.2 1066.51
      49 1059.94    68.6 1046.26    78.5 1042.56    88.3  1039.3    98.1 1032.44
   107.9 1027.33   117.7 1025.64   127.5 1025.49   147.9 1022.66   156.9 1022.24
   162.9 1022.65   166.7 1022.91   176.5  1026.3   186.3 1030.81   196.1 1032.62
   215.8 1033.34   245.2 1033.82     255 1034.63   264.8  1037.2   274.6 1042.77
   284.4 1049.69   294.2 1056.38     304 1062.54   313.8 1066.11   323.6 1067.83
#Mann= 3 , 0 , 0
       0      .1       0   147.9    .045       0   162.9      .1       0
Bank Sta=147.9,162.9
XS Rating Curve= 0 ,0
Exp/Cntr=0.3,0.1

Type RM Length L Ch R = 1 ,4608.6  ,384.3,393.1,401.9
XS GIS Cut Line= 2
     1660783.176      275959.346     1660741.093      275583.659
#Sta/Elev= 30
       0 1103.35    19.4 1090.22    29.1 1086.19    38.8 1083.28    48.5 1075.16
    77.6 1046.93    87.2 1037.23    96.9 1028.28   106.6  1023.2   116.3 1022.62
   125.5  1020.3   135.7  1018.6   140.5 1018.51   145.4 1018.42   155.1 1018.71
   164.8 1020.36   174.5 1022.62   184.2 1023.82   193.9 1023.86   222.9 1025.56
     252  1028.7   281.1 1028.61   310.2 1029.92   319.9  1032.1   329.6 1036.44
   339.3 1041.61     349 1045.42   358.6 1047.88   368.3 1051.03     378 1054.87
#Mann= 3 , 0 , 0
       0      .1       0   125.5    .045       0   140.5      .1       0
Bank Sta=125.5,140.5
XS Rating Curve= 0 ,0
Exp/Cntr=0.3,0.1

Type RM Length L Ch R = 1 ,4215.6  ,387.1,399.8,412.5
XS GIS Cut Line= 2
     1661104.716      275868.364     1661205.965      275505.202
#Sta/Elev= 30
       0 1068.34    19.3 1060.85    38.7 1053.96    48.3 1050.13      58 1045.42
    67.7 1041.61    77.3 1039.22      87 1032.46    96.7 1023.67   106.1 1015.89
     116 1014.74   121.1 1015.46   125.7 1016.11   135.3 1018.15   164.3    1018
     174  1019.6   183.7 1021.74   193.3 1022.43     203 1021.48   222.3 1018.06
     232 1016.98   251.3 1015.76     261 1016.21   270.7 1018.96     290 1032.66
   299.7  1038.5   309.3 1044.84     319 1045.59   338.3 1061.69     377 1091.42
#Mann= 3 , 0 , 0
       0      .1       0   106.1    .045       0   121.1     .06       0
#XS Ineff= 2 , 0
                           193.1         1022.51
Permanent Ineff=
       F       F
Bank Sta=106.1,121.1
XS Rating Curve= 0 ,0
Exp/Cntr=0.3,0.1

Type RM Length L Ch R = 1 ,3815.6  ,296.9,304.4,312
XS GIS Cut Line= 2
     1661337.626      276098.171     1661592.109      275867.529
#Sta/Elev= 30
       0 1068.29    19.6 1054.93    29.4 1045.29    39.2  1039.6    49.1 1034.71
    58.9 1030.97    68.7 1028.09    98.1 1013.52   107.9 1009.86   117.8 1007.49
   121.1 1007.18   127.6 1006.56   136.1 1006.57   137.4 1006.57   147.2 1009.15
     157 1010.69   196.3 1011.37   206.1 1012.12   235.5 1016.26   245.3 1017.15
   255.1 1015.66     265 1015.37   274.8 1017.34   284.6 1020.39   294.4 1025.84
   304.2  1029.8     314 1031.52   323.8 1031.76   333.6 1031.34   343.4 1029.22
#Mann= 3 , 0 , 0
       0      .1       0   121.1    .045       0   136.1     .06       0
Bank Sta=121.1,136.1
XS Rating Curve= 0 ,0
Exp/Cntr=0.3,0.1

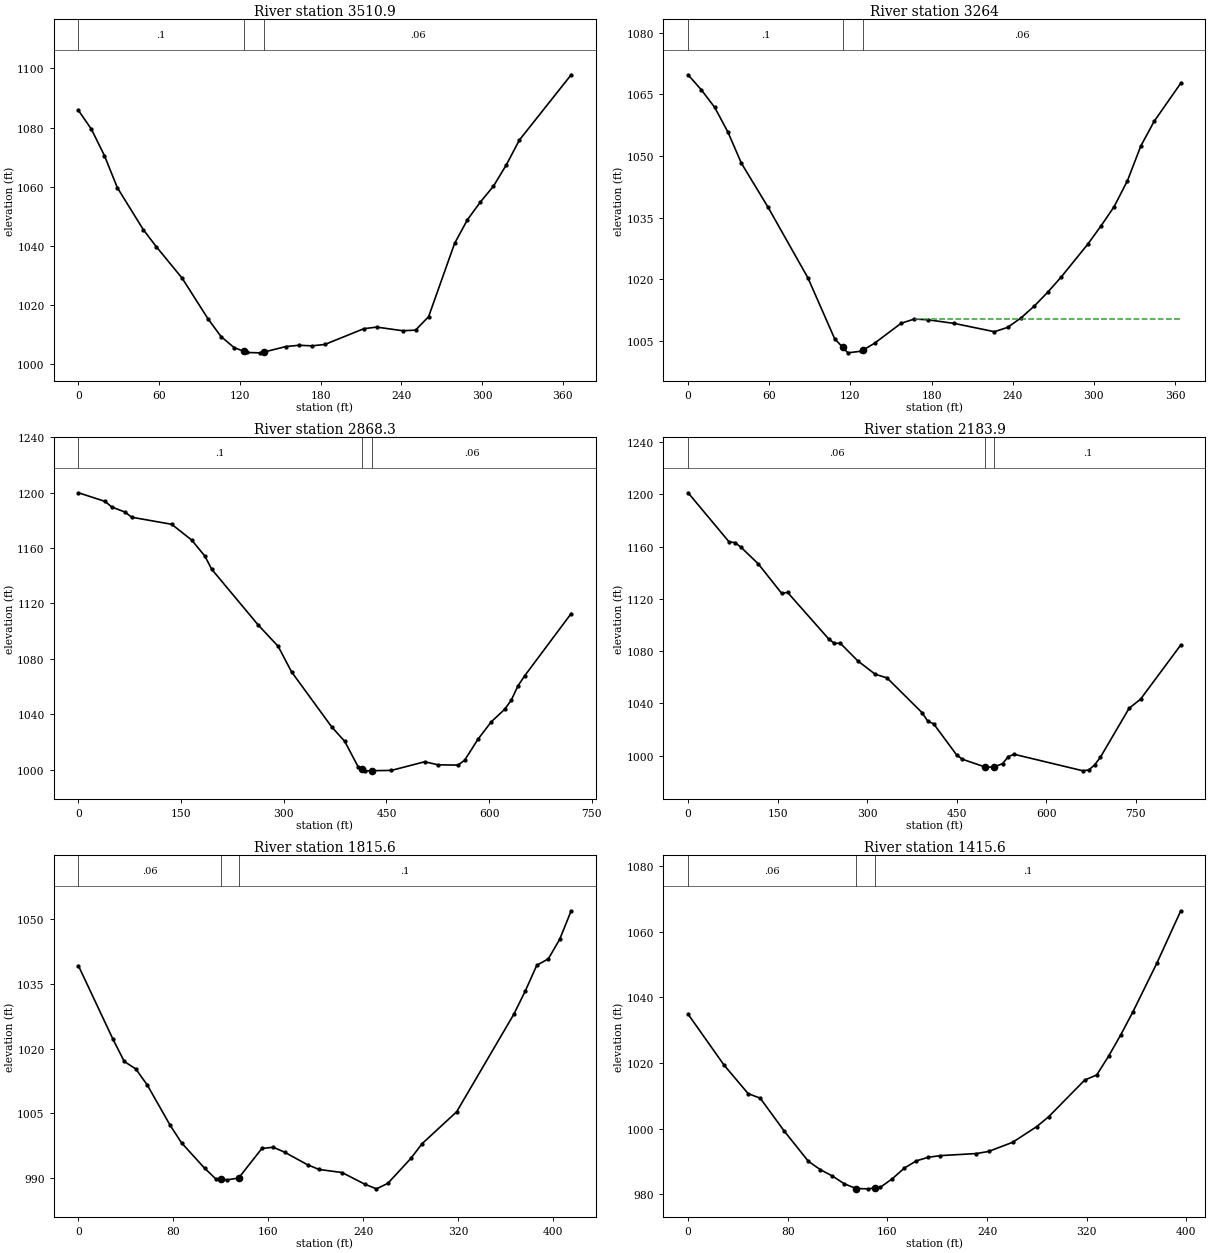
Type RM Length L Ch R = 1 ,3510.9  ,245.9,246.9,247.8
XS GIS Cut Line= 2
       1661456.7       276328.73     1661792.632      276182.605
#Sta/Elev= 30
       0 1085.78     9.6 1079.44    19.3 1070.48    28.9 1059.63    48.2 1045.42
    57.8 1039.69    77.1 1028.97    96.4 1015.16     106 1009.23   115.7 1005.48
   123.1 1004.21   125.3 1003.83     135 1003.71   138.1    1004   154.2 1005.84
   163.9 1006.27   173.5 1006.08   183.2 1006.55   212.1 1011.88   221.7 1012.43
     241  1011.2   250.6  1011.4   260.3 1015.96   279.6 1040.74   289.2 1048.81
   298.8 1054.78   308.5 1060.13   318.1 1067.38   327.8 1075.77   366.3 1097.87
#Mann= 3 , 0 , 0
       0      .1       0   123.1    .045       0   138.1     .06       0
Bank Sta=123.1,138.1
XS Rating Curve= 0 ,0
Exp/Cntr=0.3,0.1

Type RM Length L Ch R = 1 ,3264    ,403,395.7,388.5
XS GIS Cut Line= 2
     1661572.724      276541.454     1661912.348      276410.067
#Sta/Elev= 30
       0 1069.76     9.8 1066.09    19.7 1061.82    29.5 1055.78    39.4 1048.25
      59 1037.61    88.6 1020.35   108.3  1005.6   114.3 1003.48   118.1 1002.14
     128 1002.55   129.3  1002.8   137.8 1004.47   157.5 1009.34   167.3 1010.36
   177.2 1010.18   196.8 1009.29   226.4 1007.28   236.2 1008.33     246 1010.61
   255.9 1013.51   265.7 1016.83   275.6  1020.5   295.3  1028.5   305.1 1032.94
   314.9 1037.68   324.8 1044.01   334.6  1052.4   344.5 1058.43   364.2 1067.72
#Mann= 3 , 0 , 0
       0      .1       0   114.3    .045       0   129.3     .06       0
#XS Ineff= 2 , 0
                          167.85         1010.45
Permanent Ineff=
       F       F
Bank Sta=114.3,129.3
XS Rating Curve= 0 ,0
Exp/Cntr=0.3,0.1

Type RM Length L Ch R = 1 ,2868.3  ,709.5,683.5,656.7
XS GIS Cut Line= 2
     1661514.755      277129.569     1662069.861      276671.211
#Sta/Elev= 30
       0  1199.9    38.9 1193.65    48.6 1189.64    68.1 1185.94    77.8 1182.25
   136.2 1177.15   165.4 1165.78   184.8 1154.11   194.6 1144.74   262.7 1104.41
   291.8 1089.03   311.3 1070.66   369.7 1031.09   389.1  1020.4   408.6  1002.1
   414.1 1000.45   418.3  999.19   429.1   999.3   457.2   999.5   505.9 1005.75
   525.3 1003.54   554.5 1003.33   564.2 1006.82   583.7    1022   603.2  1034.6
   622.6 1043.55   632.3 1050.14   642.1 1060.46   651.8 1067.68   719.9 1112.73
#Mann= 3 , 0 , 0
       0      .1       0   414.1    .045       0   429.1     .06       0
Bank Sta=414.1,429.1
XS Rating Curve= 0 ,0
Exp/Cntr=0.3,0.1

Type RM Length L Ch R = 1 ,2183.9  ,370.8,368.6,366.4
XS GIS Cut Line= 3
     1662228.357      277465.381     1662387.554      277106.978
     1662269.322      276689.942
#Sta/Elev= 30
       0 1201.29    68.6 1163.74    78.4 1163.12    88.2 1159.78   117.6 1146.86
   156.9  1124.2   166.7 1125.01   235.3 1089.51   245.1 1085.95   254.9 1086.15
   284.3 1072.58   313.7 1062.27   333.3 1059.56   392.2 1032.83   401.8  1026.3
   411.4 1024.41     450 1000.54   459.6  997.25   497.8  991.27   512.8  991.28
     527  993.92   536.7  999.29   546.3 1001.04   661.9  988.36   671.5  989.06
   681.2  992.87   690.8  998.69     739 1036.26   758.2 1043.24   825.6 1084.74
#Mann= 3 , 0 , 0
       0     .06       0   497.8    .045       0   512.8      .1       0
#XS Ineff= 2 , 0
                          547.54         1000.75
Permanent Ineff=
       F       F
Bank Sta=497.8,512.8
XS Rating Curve= 0 ,0
Exp/Cntr=0.3,0.1

Type RM Length L Ch R = 1 ,1815.6  ,401.2,399.9,398.7
XS GIS Cut Line= 2
     1662743.757      276995.347       1662593.8      276607.958
#Sta/Elev= 30
       0 1039.11      29 1022.19    38.6    1017    48.3 1015.28      58 1011.56
    77.3 1002.24    86.9  998.18   106.3  992.33   115.9  989.82     120  989.74
   125.6  989.64     135  990.04   154.6  996.88   164.2  997.17   173.9  996.01
   193.2   993.1   202.9  992.03   222.2  991.32   241.5  988.61   251.2  987.55
   260.8  988.81   280.2  994.58   289.8  998.02   318.8 1005.35   367.1 1027.95
   376.8 1033.35   386.4 1039.25   396.1 1040.72   405.7 1045.24   415.4 1051.85
#Mann= 3 , 0 , 0
       0     .06       0     120    .045       0     135      .1       0
#XS Ineff= 2 , 0
                          163.47          997.05
Permanent Ineff=
       F       F
Bank Sta=120,135
XS Rating Curve= 0 ,0
Exp/Cntr=0.3,0.1

Type RM Length L Ch R = 1 ,1415.6  ,399.1,399.8,400.6
XS GIS Cut Line= 2
     1663132.906      276871.014     1662969.672      276510.749
#Sta/Elev= 30
       0  1034.9    28.9 1019.37    48.2 1010.71    57.9 1009.31    77.2  999.28
    96.5  990.11   106.1  987.56   115.8  985.62   125.4  983.23   134.8   981.8
   144.7   981.7   149.8  981.97   154.4  982.21     164  984.79   173.6  988.03
   183.3  990.23   192.9  991.32   202.6  991.82   231.5  992.45   241.2  993.09
   260.5  995.87   279.8 1000.64   289.4 1003.64   318.4 1014.84     328 1016.38
   337.6 1022.13   347.3  1028.6   356.9 1035.48   376.2 1050.36   395.5 1066.39
#Mann= 3 , 0 , 0
       0     .06       0   134.8    .045       0   149.8      .1       0
Bank Sta=134.8,149.8
XS Rating Curve= 0 ,0
Exp/Cntr=0.3,0.1

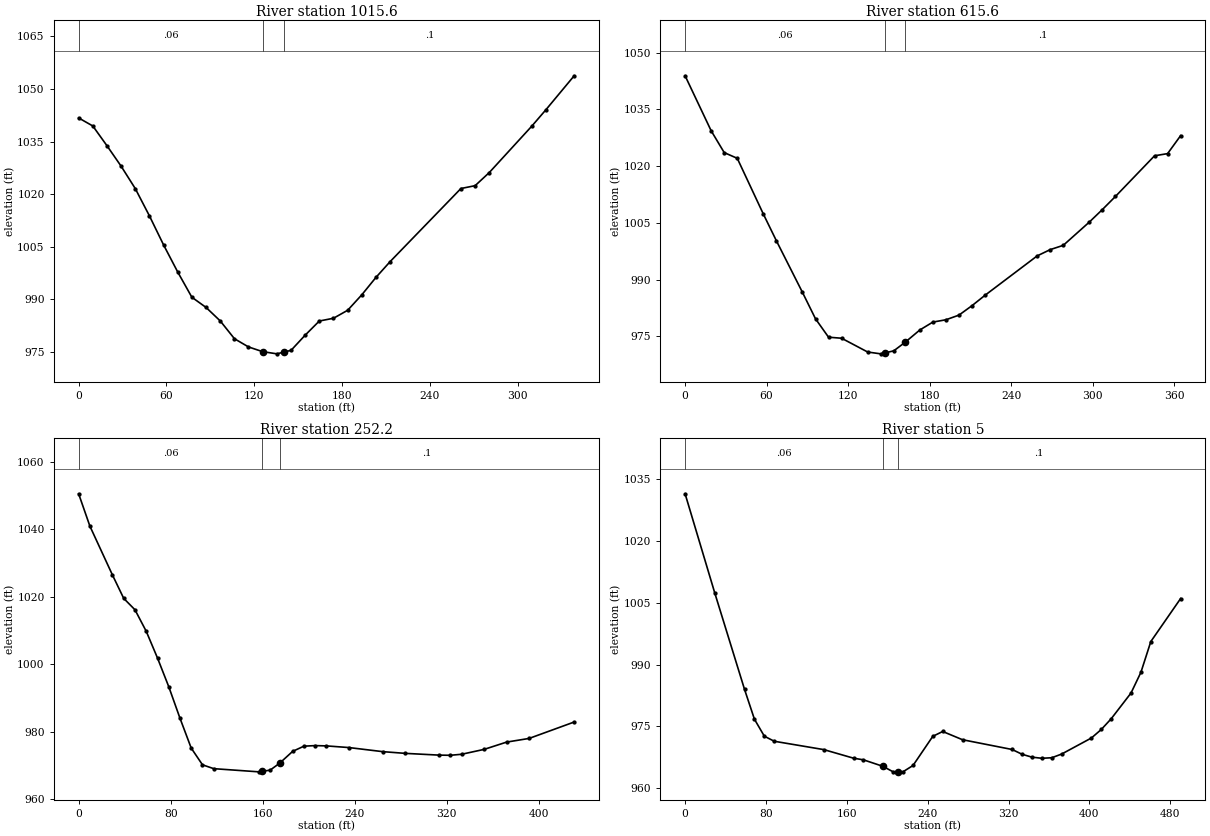
Type RM Length L Ch R = 1 ,1015.6  ,394.1,399.9,405.7
XS GIS Cut Line= 2
     1663486.543      276698.026     1663357.573      276384.812
#Sta/Elev= 30
       0 1041.74     9.7 1039.44    19.4 1033.79      29    1028    38.7  1021.6
    48.4  1013.8    58.1 1005.49    67.8  997.74    77.4   990.6    87.1  987.69
    96.8  983.84   106.5  978.77   116.1  976.43   125.7  975.09   135.5  974.46
   140.7     975   145.2  975.46   154.8  979.77   164.5  983.82   174.2  984.61
   183.9  986.89   193.6  991.32   203.2  996.25   212.9 1000.76   261.3 1021.61
     271 1022.42   280.7 1026.17   309.7 1039.38   319.4 1044.08   338.7 1053.76
#Mann= 3 , 0 , 0
       0     .06       0   125.7    .045       0   140.7      .1       0
Bank Sta=125.7,140.7
XS Rating Curve= 0 ,0
Exp/Cntr=0.3,0.1

Type RM Length L Ch R = 1 ,615.6   ,350.7,363.2,375.6
XS GIS Cut Line= 2
     1663832.951      276600.355     1663784.389      276238.796
#Sta/Elev= 30
       0 1043.89    19.2 1029.33    28.8 1023.57    38.4 1022.06    57.6 1007.32
    67.2 1000.25    86.4   986.6      96  979.61   105.6  974.74   115.2  974.47
   134.4  970.82     144  970.34   147.2   970.6   153.6  971.13   162.2  973.46
   172.8  976.65   182.4  978.74     192  979.35   201.6  980.58   211.2  983.08
   220.8  985.83   259.2  996.25   268.8  997.91   278.4  999.04   297.6  1005.2
   307.2 1008.51   316.8 1011.97   345.6 1022.73   355.2  1023.3   364.8 1028.06
#Mann= 3 , 0 , 0
       0     .06       0   147.2    .045       0   162.2      .1       0
Bank Sta=147.2,162.2
XS Rating Curve= 0 ,0
Exp/Cntr=0.3,0.1

Type RM Length L Ch R = 1 ,252.2   ,238.9,247.3,255.8
XS GIS Cut Line= 2
     1664102.255      276633.187     1664277.468      276239.507
#Sta/Elev= 30
       0 1050.45     9.8 1040.86    29.4 1026.41    39.2 1019.48      49  1016.1
    58.8 1009.72    68.6  1001.8    78.4   993.3    88.1  984.02    97.9  975.15
   107.7   970.2   117.5  969.06   156.7  968.12   159.8  968.28   166.5  968.62
   174.8  970.68   186.1  974.18   195.9  975.72   205.7  975.89   215.5   975.8
     235  975.31   264.4   974.1     284  973.59   313.4  973.07   323.2  973.02
     333  973.32   352.6  974.77   372.2  976.93   391.7  978.01   430.9  982.87
#Mann= 3 , 0 , 0
       0     .06       0   159.8    .045       0   174.8      .1       0
#XS Ineff= 2 , 0
                          205.78          975.71
Permanent Ineff=
       F       F
Bank Sta=159.8,174.8
XS Rating Curve= 0 ,0
Exp/Cntr=0.3,0.1

Type RM Length L Ch R = 1 ,5       ,4.6,5,5.4
XS GIS Cut Line= 2
     1664231.785      276750.896     1664580.908      276406.709
#Sta/Elev= 30
       0 1031.44    29.4 1007.34    58.8  983.99    68.6  976.75    78.4  972.63
    88.2   971.4   137.3  969.37   166.7  967.29   176.5  966.89   195.6  965.33
   205.9  963.98   210.6  963.99   215.7  964.01   225.5  965.52   245.1   972.6
   254.9  973.77   274.5  971.77   323.6   969.4   333.4  968.24   343.2  967.54
     353  967.27   362.8   967.4   372.6   968.3     402  972.19   411.8  974.26
   421.6  976.86   441.2   983.1     451  988.13   460.8  995.59   490.3 1006.03
#Mann= 3 , 0 , 0
       0     .06       0   195.6    .045       0   210.6      .1       0
#XS Ineff= 2 , 0
                          255.49           973.4
Permanent Ineff=
       F       F
Bank Sta=195.6,210.6
XS Rating Curve= 0 ,0
Exp/Cntr=0.3,0.1

Chan Stop Cuts=-1
Use User Specified Reach Order=0
Composite Channel Slope=5